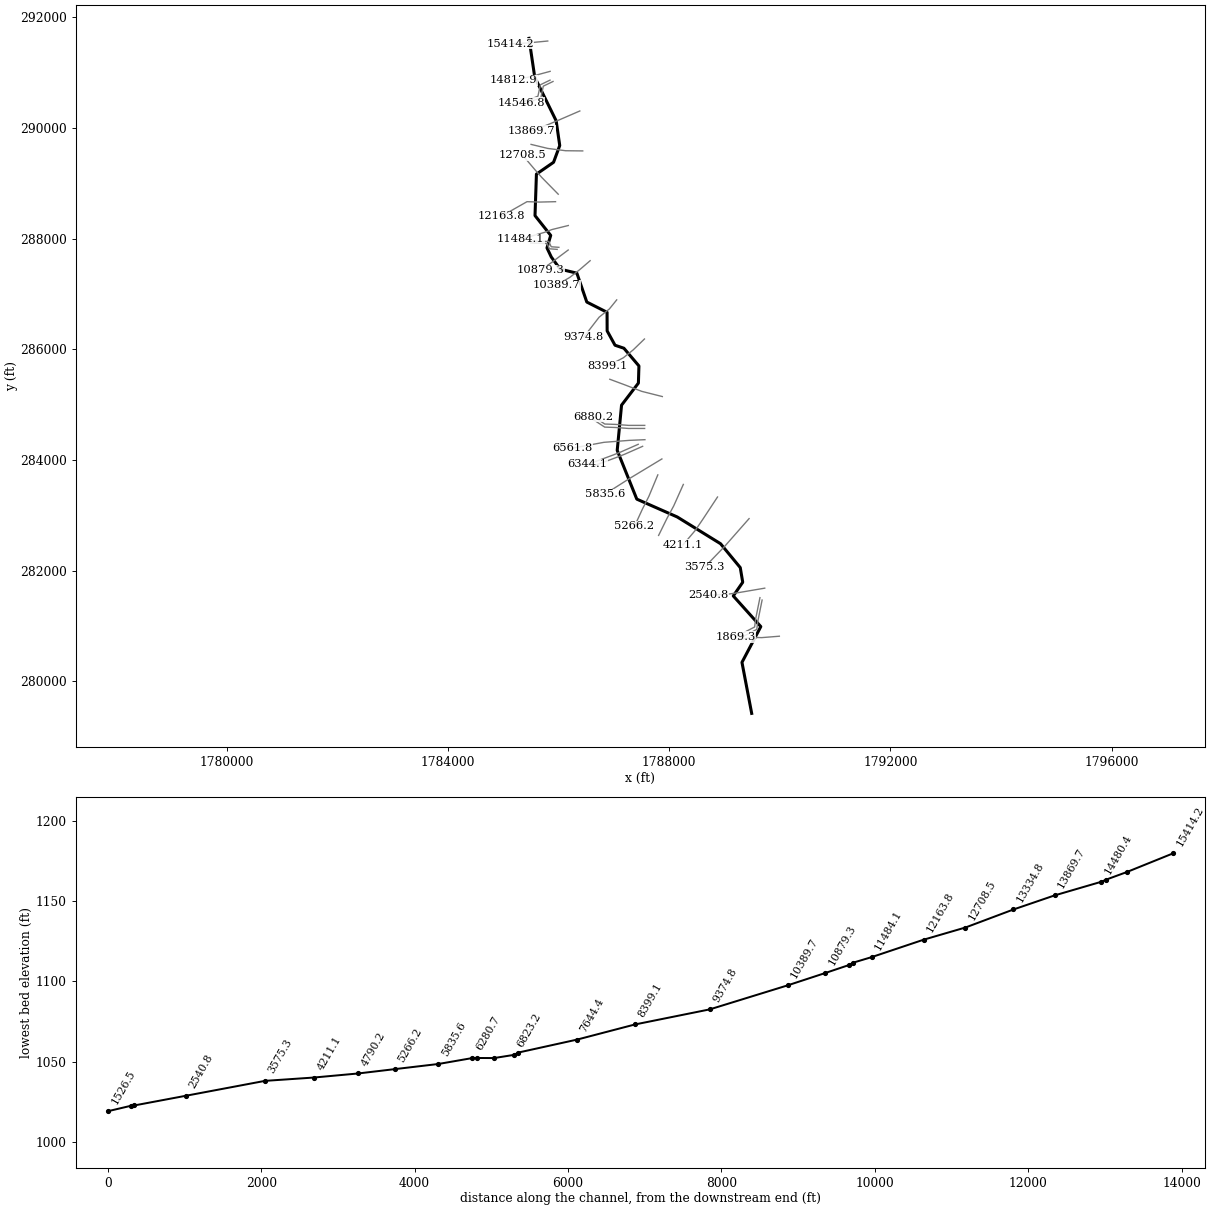
--- BerryRun.prj (project) ---

Proj Title=BerryRun
Current Plan=p01
Default Exp/Contr=0,0
English Units
Geom File=g01
Flow File=f01
Plan File=p01
BEGIN DESCRIPTION:
END DESCRIPTION:
DSS Export Rating Curves= 0
DSS Export Rating Curve Sorted= 0
DSS Export Volume Flow Curves= 0
DXF OffsetX= 0
DXF OffsetY= 0
DXF ScaleX= 0
DXF ScaleY= 0

--- BerryRun.p01 (plan) ---

Plan Title=Floodplain
Program Version=4.00
Geom File=g01
Flow File=f01
K Sum by GR=0
Std Step Tol=0.01
Critical Tol=0.01
Num of Std Step Trials=20
Max Error Tol=0.3
Flow Tol Ratio=0.001
Split Flow NTrial=30
Split Flow Tol=0.02
Split Flow Ratio=0.02
Log Output Level=0
Friction Slope Method=1
Unsteady Friction Slope Method=2
Unsteady Bridges Friction Slope Method=1
Global Log Level=0
CheckData=False
Run HTab=0
Run UNet=0
Run PostProcess=0
UNET Theta=0
UNET Theta Warmup=0
UNET ZTol=0
UNET ZSATol=0
UNET MxIter=0
UNET MaxInSteps=0
UNET DtIC=0
UNET DtMin=0
UNET MaxCRTS=0
UNET WFStab=0
UNET SFStab=0
UNET WFX=0
UNET SFX=0
UNET DSS MLevel=0
UNET DZMax Abort=0
UNET Convert EG Bridges=0
UNET Use Existing IB Tables=0
UNET Froude Limit=0
UNET Froude Power=0
Write IC File=0
Echo Input=False
Echo Output=False
Write Detailed=0

--- BerryRun.f01 (steady flow) ---

Flow Title=NFF Regression Equation
Program Version=4.10
Number of Profiles= 1
Profile Names=P100yr
River Rch & RM=BerryRun,Main            ,15414.2
     338
River Rch & RM=BerryRun,Main            ,12708.5
     461
River Rch & RM=BerryRun,Main            ,10389.7
     641
River Rch & RM=BerryRun,Main            ,8399.1
     733
River Rch & RM=BerryRun,Main            ,6880.2
     794
River Rch & RM=BerryRun,Main            ,6561.8
    1090
River Rch & RM=BerryRun,Main            ,4790.2
    1130
River Rch & RM=BerryRun,Main            ,191.4
    1245
Boundary for River Rch & Prof#=BerryRun,Main            , 1
Up Type= 0
Dn Type= 3
Dn Slope=0.00305
DSS Import GetInterval= 0
DSS Import GetPeak= 0
DSS Import FillOption= 0

--- BerryRun.g01 (geometry) ---

Geom Title=USGS 10m DEM
Program Version=4.10

River Reach=BerryRun        ,Main
Reach XY= 30
     1785465.932      291617.835      1785569.88      290915.702
     1785957.208      290127.688     1786021.668      289680.803
     1785909.986      289378.382     1785600.264      289163.799
     1785574.743      288414.667     1785858.597      288057.375
     1785790.889      287831.334     1785869.014       287666.75
     1786029.431      287447.479     1786331.514      287375.084
     1786510.811      286853.252     1786877.359      286667.786
     1786878.704      286332.028     1787021.108      286072.924
     1787181.699      286018.671     1787453.333       285698.81
     1787443.784      285388.915     1787139.278       284990.33
     1787060.753      284172.918     1787414.749      283292.379
     1788145.397      282970.345     1788928.934       282486.59
      1789285.19      282055.176     1789329.784      281790.604
     1789158.861      281543.297     1789656.643      280989.255
     1789316.087      280343.188     1789491.769      279421.426

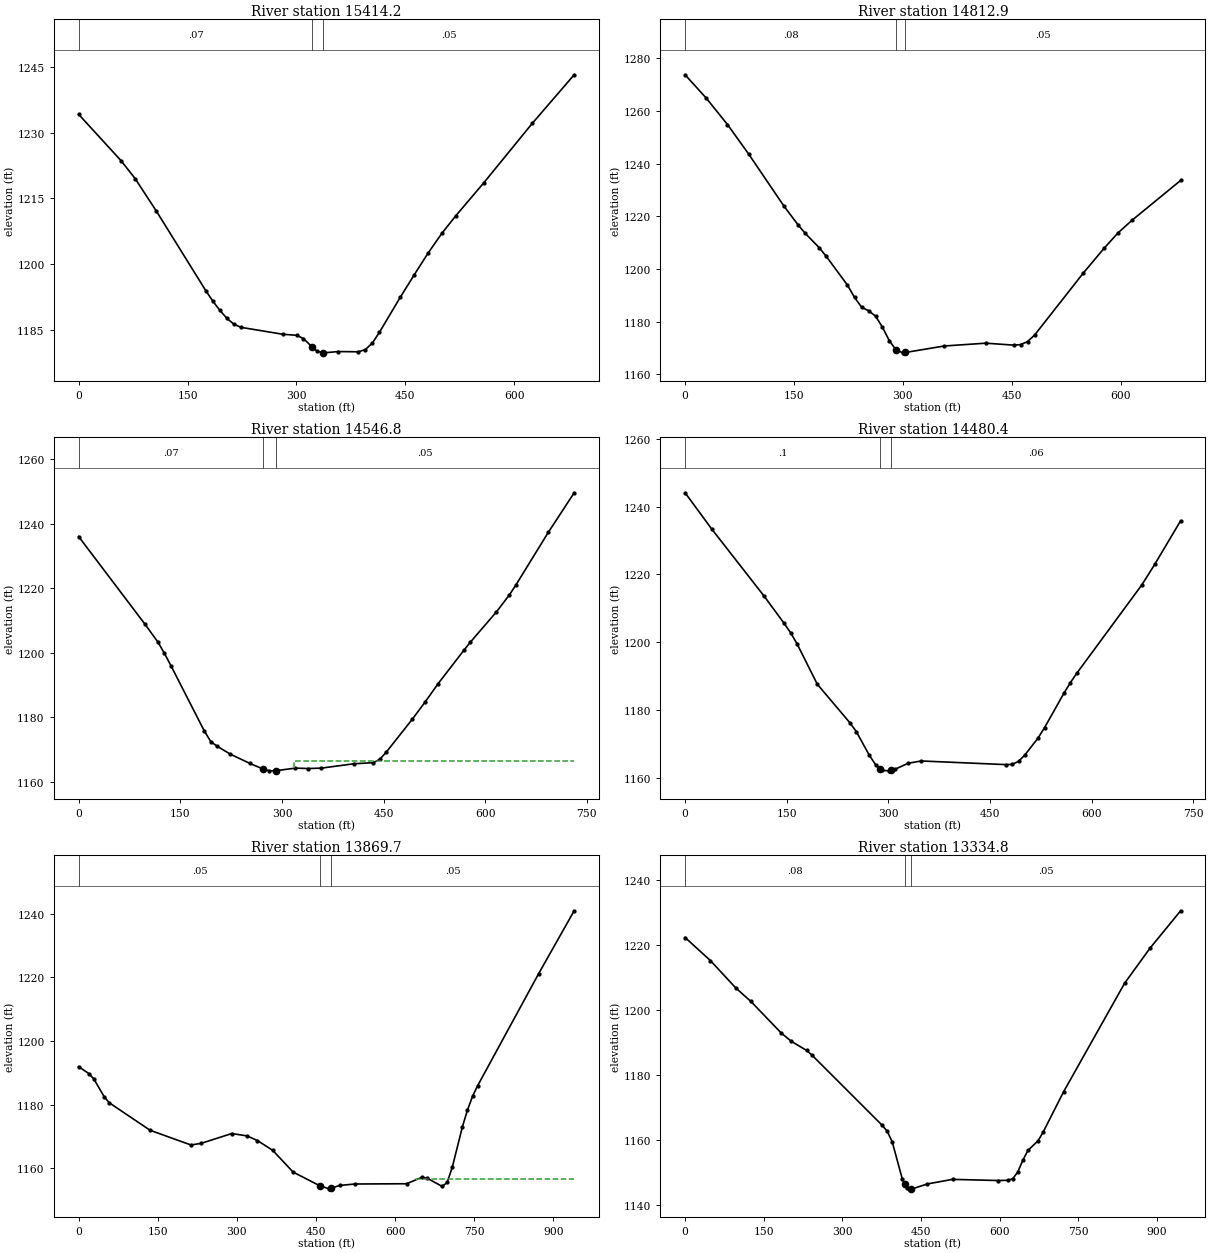
Type RM Length L Ch R = 1 ,15414.2 ,597.4,601.3,604.9
XS GIS Cut Line= 4
     1785805.009       291569.33     1785553.273      291545.025
     1785421.329      291532.872     1785124.454      291518.983
#Sta/Elev= 30
       0 1234.19    58.4 1223.62    77.8 1219.53     107 1212.12   175.1 1193.95
   184.8 1191.55   194.5 1189.45   204.3  1187.6     214 1186.27   223.7 1185.56
   281.3 1183.98   300.2 1183.75   309.7    1183   321.9 1181.04   328.6 1180.08
   336.9 1179.78   338.1 1179.74     357 1180.03   385.4 1179.98     395 1180.48
   404.6 1181.98   414.2 1184.39   442.9 1192.39   462.1 1197.51   481.3 1202.49
   500.4 1207.04   519.6 1211.04     558 1218.54   625.1 1232.17   682.6 1243.22
#Mann= 3 , 0 , 0
       0     .07       0   321.9    .045       0   336.9     .05       0
Bank Sta=321.9,336.9
XS Rating Curve= 0 ,0
Exp/Cntr=0.3,0.1

Type RM Length L Ch R = 1 ,14812.9 ,213.1,266.1,294.8
XS GIS Cut Line= 4
     1785848.175      291021.371     1785603.981      290955.563
     1785475.892      290921.648     1785185.455      290858.609
#Sta/Elev= 30
       0 1273.75    29.2 1264.86    58.4 1254.85    87.5 1243.67   136.2 1223.86
   155.6 1216.76   165.4 1213.55   184.8 1208.06   194.5 1204.77   223.7 1193.84
   233.4 1189.18   243.2 1185.46   252.9  1184.1   262.4 1182.08   271.8 1177.89
   281.3 1172.76   290.8 1169.15   300.2 1168.14   303.3 1168.27     357 1170.74
   414.2 1171.81   452.5 1171.07   462.1 1171.26   471.7 1172.41   481.3 1174.85
   548.4  1198.4   577.2 1207.87   596.3 1213.68   615.5 1218.46   682.6 1233.62
#Mann= 3 , 0 , 0
       0     .08       0   290.8    .045       0   303.3     .05       0
Bank Sta=290.8,303.3
XS Rating Curve= 0 ,0
Exp/Cntr=0.3,0.1

Type RM Length L Ch R = 1 ,14546.8 ,92.5,66.4,67.9
XS GIS Cut Line= 4
     1785846.676      290862.733      1785670.93      290778.309
     1785627.528      290571.712     1785324.576      290453.656
#Sta/Elev= 30
       0 1236.02    97.5 1208.99     117 1203.35   126.7 1199.82   136.5 1195.91
   185.2 1175.92     195 1172.53   204.6 1171.07   223.8 1168.65   252.6 1165.78
   271.7 1164.08   281.3 1163.48   290.9 1163.52   319.7 1164.32   338.9  1164.2
   358.1 1164.32   406.1 1165.67   434.8 1166.01   444.3 1167.04   453.9 1169.26
   492.2 1179.42   511.3  1184.8   530.4 1190.46   568.6 1200.85   578.2 1203.36
   616.5 1212.69   635.6 1217.95   645.2 1221.03     693 1237.31   731.2 1249.57
#Mann= 3 , 0 , 0
       0     .07       0   271.7    .045       0   290.9     .05       0
#XS Ineff= 2 , 0
                          317.98         1166.48
Permanent Ineff=
       F       F
Bank Sta=271.7,290.9
XS Rating Curve= 0 ,0
Exp/Cntr=0.3,0.1

Type RM Length L Ch R = 1 ,14480.4 ,633.1,610.7,583.2
XS GIS Cut Line= 4
     1785900.322      290838.254     1785724.576       290753.83
     1785681.173      290547.233     1785378.222      290429.177
#Sta/Elev= 30
       0 1244.07      39 1233.46     117 1213.49   146.2 1205.55     156 1202.72
   165.7 1199.34     195 1187.64     243 1176.29   252.6 1173.67   271.7 1166.72
   281.3 1163.83   288.1 1162.71   290.9 1162.25   300.5 1162.08   303.1 1162.22
   310.1 1162.58   329.3 1164.32   348.5 1164.99     473 1163.92   482.6 1163.98
   492.2  1164.9   501.7 1166.84   520.8 1171.75   530.4 1174.82   559.1    1185
   568.6 1188.12   578.2 1190.92   673.8 1216.87     693 1222.97   731.2 1235.82
#Mann= 3 , 0 , 0
       0      .1       0   288.1    .045       0   303.1     .06       0
#XS Ineff= 2 , 0
                          348.16         1164.97
Permanent Ineff=
       F       F
Bank Sta=288.1,303.1
XS Rating Curve= 0 ,0
Exp/Cntr=0.3,0.1

Type RM Length L Ch R = 1 ,13869.7 ,546.6,534.9,522.5
XS GIS Cut Line= 4
     1786384.871      290305.441     1786011.607      290143.983
     1785822.371      290064.122     1785516.815      289946.066
#Sta/Elev= 30
       0 1191.94    19.4 1189.76      29 1188.05    48.4 1182.49    58.1 1180.59
   135.6 1171.95     213 1167.34   232.4 1167.86   290.5 1170.94   319.5 1170.18
   338.9 1168.74     368 1165.66   406.7 1158.83   458.3 1154.45   475.2 1153.57
  479.23 1153.79   494.7 1154.63   524.1 1155.09   621.7 1155.17   650.6 1157.16
   660.3 1156.96   689.2 1154.34   698.8 1155.57   708.4  1160.3   727.7 1173.06
   737.3 1178.32     747 1182.67   756.6 1185.97   872.2 1221.12   939.6 1240.88
#Mann= 3 , 0 , 0
       0     .05       0   458.3    .045       0  479.23     .05       0
#XS Ineff= 2 , 0
                          640.34         1156.62
Permanent Ineff=
       F       F
Bank Sta=458.3,479.23
XS Rating Curve= 0 ,0
Exp/Cntr=0.3,0.1

Type RM Length L Ch R = 1 ,13334.8 ,640.9,626.3,610.5
XS GIS Cut Line= 4
     1786437.388      289583.653      1786128.36      289587.125
     1785805.443      289628.792      1785503.36      289701.709
#Sta/Elev= 30
       0  1222.3    48.3 1215.19    96.6 1206.77   125.6 1202.58   183.5 1192.85
   202.8 1190.29   231.8 1187.49   241.4 1186.15   376.1  1164.4   385.7 1162.56
   395.2 1159.28   414.4 1147.85  419.08 1146.46     424    1145   431.1 1144.87
   433.5 1144.83   462.3 1146.34   510.2 1147.75   596.3  1147.4   615.5 1147.46
   625.1 1147.95   634.6    1150   644.4 1153.66   654.1 1156.69   673.5 1159.66
   683.2 1162.36     722 1174.72   838.6 1208.23   887.1 1219.04   945.4 1230.54
#Mann= 3 , 0 , 0
       0     .08       0  419.08    .045       0   431.1     .05       0
Bank Sta=419.08,431.1
XS Rating Curve= 0 ,0
Exp/Cntr=0.3,0.1

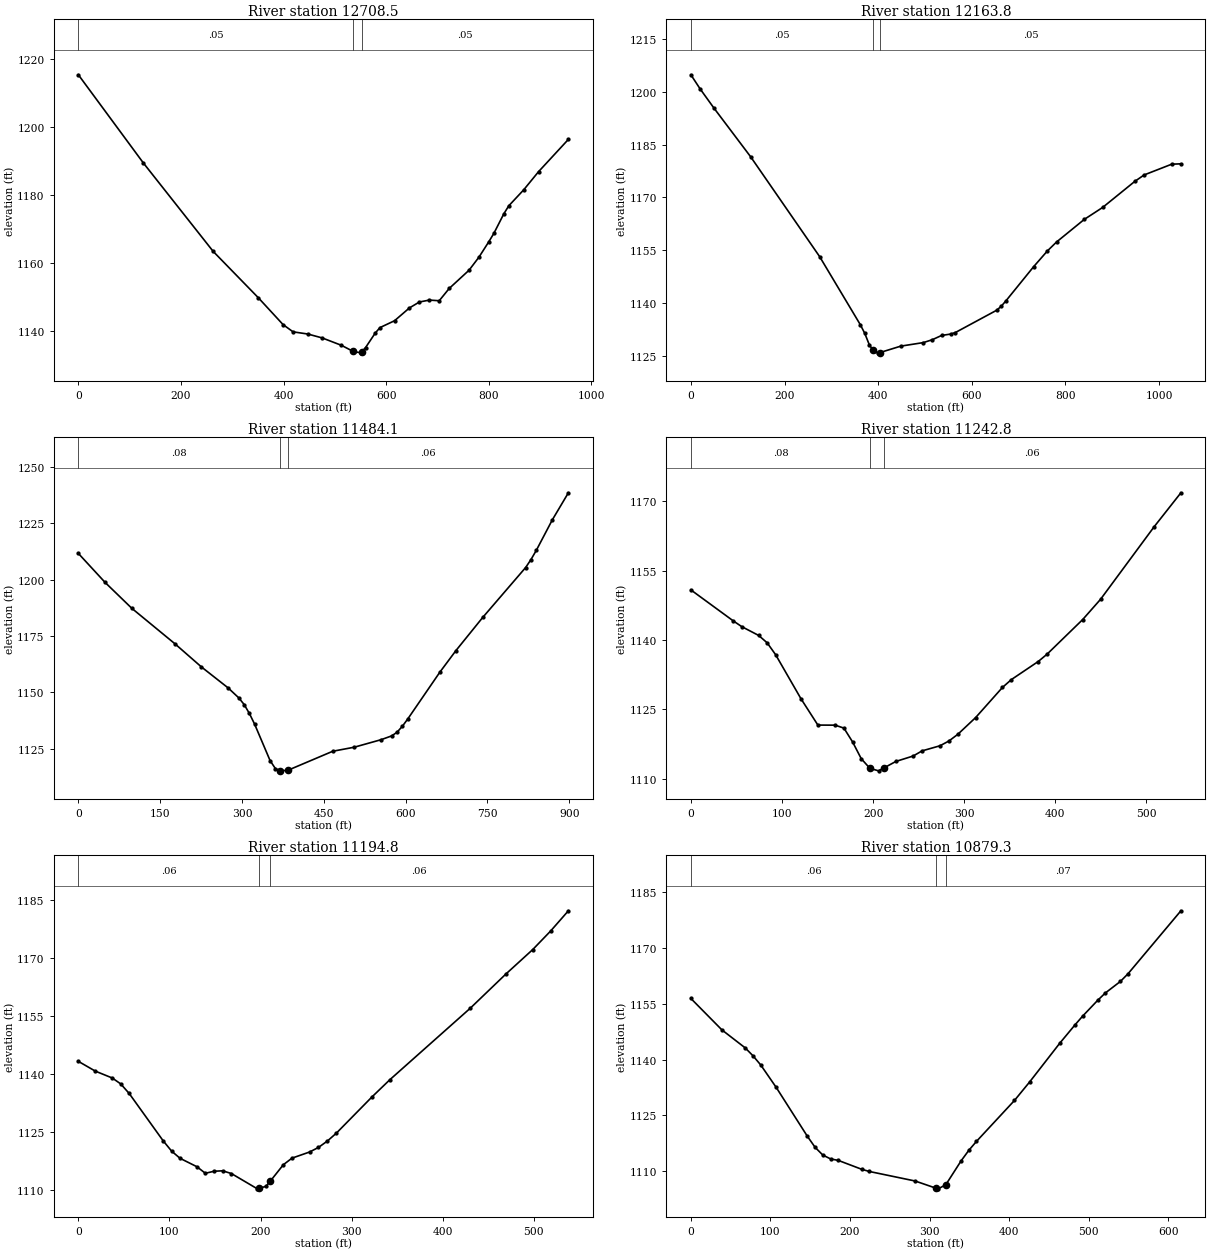
Type RM Length L Ch R = 1 ,12708.5 ,525.7,544.7,562.9
XS GIS Cut Line= 4
     1785994.246      288801.969     1785693.898      289107.525
     1785575.843      289241.205     1785350.148       289506.83
#Sta/Elev= 30
       0 1215.25   126.6 1189.38   262.9 1163.38   350.6 1149.82   399.2 1141.88
   418.7 1139.76   447.2 1139.13   475.4 1137.98   512.9 1135.81   535.9 1134.01
   550.5  1133.6  552.39 1133.92   559.9 1135.13   578.6 1139.36     588 1141.01
   616.5 1143.03   645.5 1146.79   664.9 1148.53   684.3 1149.09   703.6  1148.9
     723  1152.5   761.7 1157.86   781.1 1161.71   800.4 1166.26   810.1 1168.68
   829.5 1174.41   839.2 1176.78   868.2 1181.45   897.3 1186.81   955.4 1196.28
#Mann= 3 , 0 , 0
       0     .05       0   535.9    .045       0  552.39     .05       0
Bank Sta=535.9,552.39
XS Rating Curve= 0 ,0
Exp/Cntr=0.3,0.1

Type RM Length L Ch R = 1 ,12163.8 ,672.8,679.7,686
XS GIS Cut Line= 4
     1785945.634      288666.553     1785660.912      288659.608
     1785430.009      288666.553     1784968.204        288404.4
#Sta/Elev= 30
       0 1204.74    19.6 1200.77    49.1 1195.34   127.7 1181.52     275 1153.27
   361.8 1134.02   371.4 1131.55   381.1 1128.32   389.2  1126.7   390.7  1126.4
   400.3 1126.02   404.2 1126.11   448.4 1127.92   496.6 1128.92   515.8 1129.74
   535.5 1130.94   555.2 1131.34     565 1131.77   653.5  1138.1   663.3 1139.26
   673.2 1140.77   732.2 1150.41   761.7 1154.89   781.3 1157.42   840.3 1163.79
   879.7 1167.19   948.5 1174.58   968.2 1176.38  1027.2 1179.43  1046.8 1179.53
#Mann= 3 , 0 , 0
       0     .05       0   389.2    .045       0   404.2     .05       0
Bank Sta=389.2,404.2
XS Rating Curve= 0 ,0
Exp/Cntr=0.3,0.1

Type RM Length L Ch R = 1 ,11484.1 ,275.9,241.3,202.8
XS GIS Cut Line= 4
     1786176.537      288235.997     1785881.398       288163.08
     1785747.718      288112.733      1785313.69      287987.733
#Sta/Elev= 30
       0 1211.69      49 1198.82    98.1  1187.3   176.5 1171.68   225.6 1161.29
   274.6 1151.97   294.2 1147.54     304 1144.58   313.5 1140.66   323.1 1135.92
   351.6 1119.66   361.2 1116.17   369.4 1115.28   370.7 1115.14   384.4 1115.41
   466.5 1123.84   505.8 1125.63   554.9 1128.96   574.5 1130.66   584.3 1132.28
   594.1 1134.94     604 1138.18   662.9 1158.98   692.3 1168.54   741.4 1183.25
     820 1205.39   829.8 1208.92   839.6 1213.02   869.1 1226.62   898.5 1238.62
#Mann= 3 , 0 , 0
       0     .08       0   369.4    .045       0   384.4     .06       0
Bank Sta=369.4,384.4
XS Rating Curve= 0 ,0
Exp/Cntr=0.3,0.1

Type RM Length L Ch R = 1 ,11242.8 ,48.1,48,51.6
XS GIS Cut Line= 4
     1786006.615       287841.77     1785867.553      287852.099
     1785824.063      287947.152      1785530.27      287956.787
#Sta/Elev= 30
       0 1150.82    46.5 1144.12    55.8 1142.88    74.4 1140.97    83.7 1139.38
      93 1136.81   120.8 1127.29   139.4 1121.58   158.4 1121.56     168 1120.92
   177.5 1117.93     187 1114.31   196.5 1112.22     206 1111.68   211.5 1112.27
     225 1113.71     244 1114.89   253.8    1116   273.4  1117.1   283.2 1118.13
     293 1119.58   312.6 1123.21     342 1129.72   351.8 1131.42   381.2 1135.32
     391 1136.92   430.1 1144.41   449.7 1148.79   508.5 1164.48   537.9 1171.83
#Mann= 3 , 0 , 0
       0     .08       0   196.5    .045       0   211.5     .06       0
Bank Sta=196.5,211.5
XS Rating Curve= 0 ,0
Exp/Cntr=0.3,0.1

Type RM Length L Ch R = 1 ,11194.8 ,274,315.5,356.8
XS GIS Cut Line= 4
     1785975.148      287804.877     1785836.086      287815.207
     1785792.596      287910.259     1785498.803      287919.895
#Sta/Elev= 30
       0 1143.33    18.6  1140.8    37.2 1139.02    46.5 1137.49    55.8 1135.01
      93 1122.78   102.3  1120.1   111.6 1118.22   130.2 1116.03   139.4 1114.34
     149 1114.87   158.4 1114.98     168 1114.27   196.5 1110.31   197.8  1110.4
     206 1110.96  210.51 1112.25     225 1116.55   234.5 1118.26   253.8 1119.85
   263.6 1121.04   273.4  1122.7   283.2 1124.73   322.4 1134.14     342 1138.59
   430.1 1157.07   469.3 1165.95   498.7 1172.27   518.3 1177.06   537.9 1182.33
#Mann= 3 , 0 , 0
       0     .06       0   197.8    .045       0  210.51     .06       0
Bank Sta=197.8,210.51
XS Rating Curve= 0 ,0
Exp/Cntr=0.3,0.1

Type RM Length L Ch R = 1 ,10879.3 ,489.4,489.6,487.4
XS GIS Cut Line= 4
     1786174.801      287793.289     1786002.926      287664.816
     1785872.718      287565.858     1785678.038      287429.473
#Sta/Elev= 30
       0 1156.41      39 1147.96    68.3 1143.12      78 1141.01    87.8 1138.53
   107.3 1132.48   146.3 1119.39   156.1  1116.4   165.8 1114.32   175.6 1113.28
   185.3 1112.88   214.6  1110.5   224.2 1109.91   281.9 1107.34   308.6 1105.37
   310.8 1105.24   320.4 1106.36   339.6 1112.77   349.3  1115.6   358.9    1118
   406.6 1128.99   425.7 1133.97   463.7 1144.42   482.7 1149.31   492.2 1151.64
   511.2 1155.91   520.8 1157.88   539.8    1161   549.3 1163.04   615.8 1179.98
#Mann= 3 , 0 , 0
       0     .06       0   308.6    .045       0   320.4     .07       0
Bank Sta=308.6,320.4
XS Rating Curve= 0 ,0
Exp/Cntr=0.3,0.1

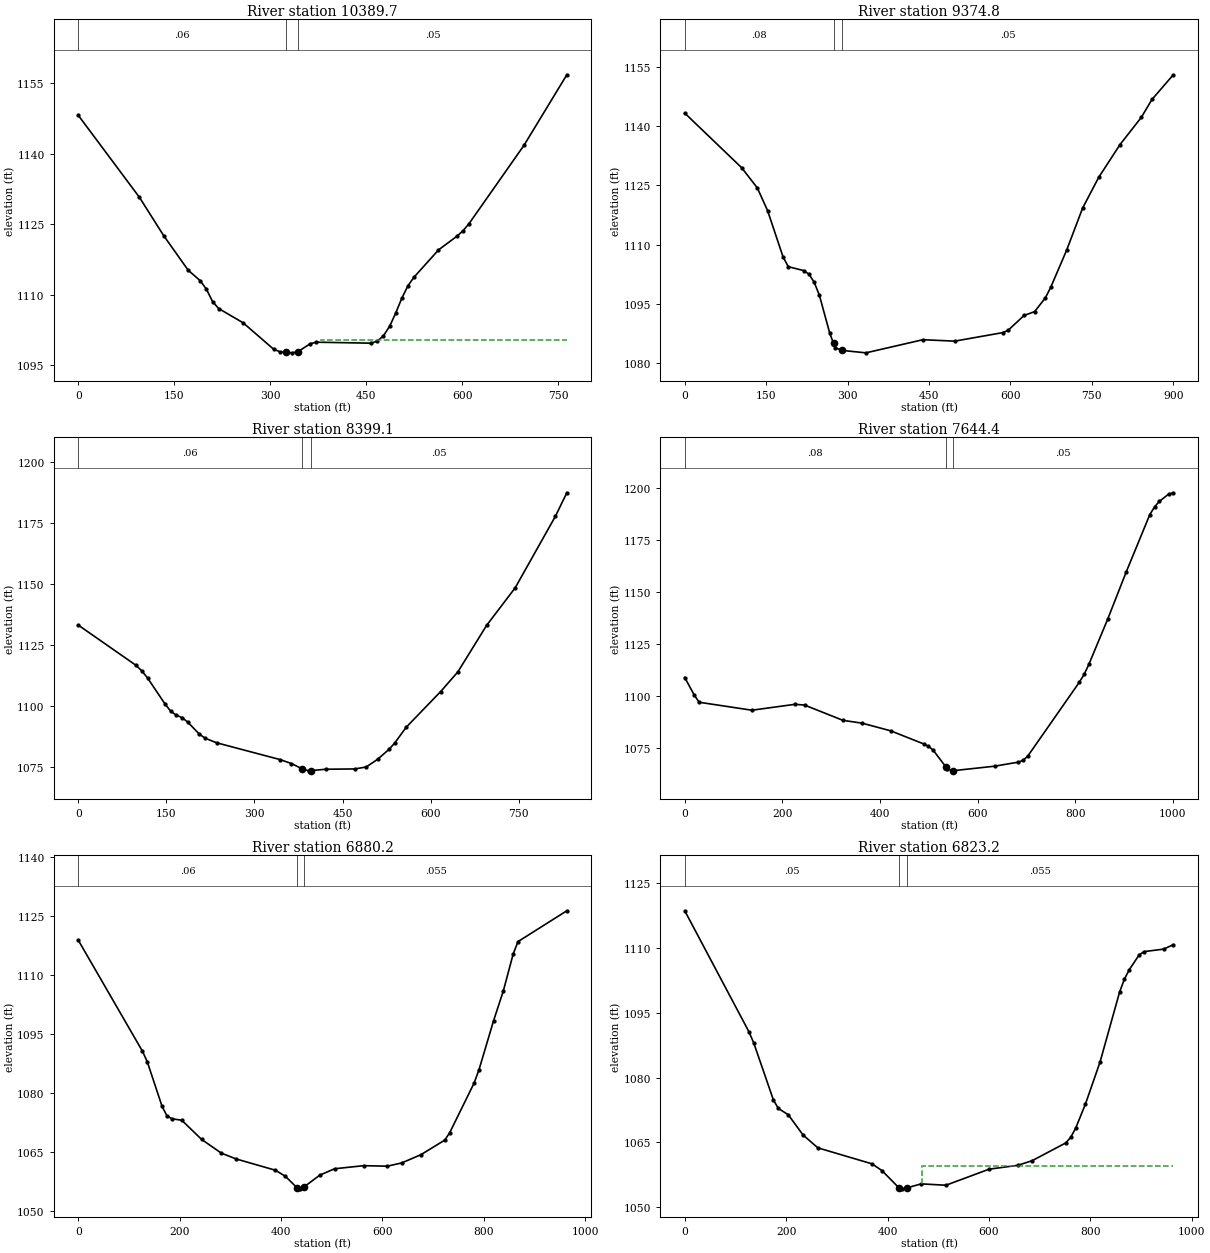
Type RM Length L Ch R = 1 ,10389.7 ,1013.1,1014.9,1018.2
XS GIS Cut Line= 4
     1786571.267      287600.046     1786383.134      287438.688
     1786202.579      287298.063     1785955.381      287153.431
#Sta/Elev= 30
       0  1148.2    95.3 1130.76   133.5 1122.53   171.6 1115.19   190.6 1112.93
   200.2 1111.12   209.7 1108.51   219.2 1107.02   257.4 1103.98   305.1 1098.35
   314.6 1097.82   324.1 1097.65   333.7 1097.57   343.3 1097.83   362.3 1099.51
   371.8 1099.84   457.6 1099.63   467.2 1100.08   476.7 1101.21   486.3 1103.23
   495.8 1106.04   505.4 1109.23   514.9 1111.86   524.4  1113.7   562.6  1119.5
   591.3 1122.42   600.8 1123.57   610.4 1125.12   696.3 1141.83   763.1 1156.84
#Mann= 3 , 0 , 0
       0     .06       0   324.1    .045       0   343.3     .05       0
#XS Ineff= 2 , 0
                          379.75         1100.39
Permanent Ineff=
       F       F
Bank Sta=324.1,343.3
XS Rating Curve= 0 ,0
Exp/Cntr=0.3,0.1

Type RM Length L Ch R = 1 ,9374.8  ,976.1,975.7,974.2
XS GIS Cut Line= 4
     1787051.537      286892.247     1786919.593      286729.053
     1786733.829      286579.747     1786457.787      286222.108
#Sta/Elev= 30
       0 1143.26   104.9 1129.44   133.6 1124.36   152.6  1118.6   181.2 1106.85
   190.8 1104.42   219.4 1103.41   228.9 1102.51   238.5 1100.45     248  1097.2
   267.1 1087.59  274.03 1085.01   276.6 1083.96  289.39 1083.24   333.8 1082.62
   438.7 1085.94   497.3 1085.58   585.7 1087.73   595.5 1088.29     625 1092.07
   644.6 1093.05   664.3 1096.53   674.1 1099.16   703.5 1108.59     733 1119.25
   762.5 1126.99   801.8  1135.3     841 1142.17   860.7 1146.71     900 1152.96
#Mann= 3 , 0 , 0
       0     .08       0  274.03    .045       0  289.39     .05       0
Bank Sta=274.03,289.39
XS Rating Curve= 0 ,0
Exp/Cntr=0.3,0.1

Type RM Length L Ch R = 1 ,8399.1  ,778.2,754.7,731
XS GIS Cut Line= 4
     1787553.273       286185.65     1787348.412      285987.733
     1787173.065      285847.108     1786888.343      285696.066
#Sta/Elev= 30
       0 1133.08    98.2 1116.58     108 1114.33   117.9 1111.39   147.3 1100.82
   157.2 1097.76     167 1096.06   176.8 1095.09   186.6 1093.18   206.3 1088.26
   216.1 1086.61   235.7 1084.73   343.5 1077.85     363 1076.22   381.2 1074.04
   392.4 1073.22   396.2 1073.32   421.7 1073.88   470.5    1074   490.1 1074.78
   509.6 1077.94   529.2 1082.06   538.9 1084.68   558.4 1091.13   617.1  1105.8
   646.4 1113.89   695.2 1132.93     744 1148.42   812.4 1177.77   831.9 1187.44
#Mann= 3 , 0 , 0
       0     .06       0   381.2    .045       0   396.2     .05       0
Bank Sta=381.2,396.2
XS Rating Curve= 0 ,0
Exp/Cntr=0.3,0.1

Type RM Length L Ch R = 1 ,7644.4  ,756.7,764.2,770.5
XS GIS Cut Line= 4
      1787876.19      285145.719     1787504.662      285239.469
     1787206.051      285354.053     1786926.537      285458.219
#Sta/Elev= 30
       0 1108.77    19.6 1100.27    29.5 1096.86   137.6 1093.02     226 1095.87
   245.6  1095.5   324.2 1088.14   363.5 1086.78   421.9  1083.1   489.8 1076.77
   499.5 1075.64   509.2 1073.74   535.4 1065.63   538.2 1064.84   547.9  1063.8
   550.4 1063.88   635.2 1066.04   683.6 1067.99   693.3 1068.82     703 1070.89
   808.9 1106.58   818.5 1110.25   828.1 1115.06   866.6 1136.78   905.1 1159.83
   953.2 1187.34   962.8    1191   972.4 1193.64   991.7 1197.17  1001.3 1197.83
#Mann= 3 , 0 , 0
       0     .08       0   535.4    .045       0   550.4     .05       0
Bank Sta=535.4,550.4
XS Rating Curve= 0 ,0
Exp/Cntr=0.3,0.1

Type RM Length L Ch R = 1 ,6880.2  ,57,57,56.4
XS GIS Cut Line= 5
     1787558.482      284624.886     1787266.815      284624.886
     1787034.176      284642.247     1786836.259      284649.191
     1786634.871      284781.136
#Sta/Elev= 30
       0 1118.96   126.4 1090.78   136.1 1088.06   165.3 1076.72     175 1074.29
   184.7 1073.57   204.2 1073.18   243.1 1068.34     282 1064.84   311.1 1063.36
   388.9 1060.48   408.3 1058.96   431.2 1056.07   437.5 1055.75   446.2 1056.32
   476.4 1059.23   505.5 1060.85   562.7 1061.64   609.8 1061.51   638.1 1062.34
   675.8 1064.42     723 1068.14   732.6 1069.99   780.8 1082.62   790.4 1085.99
   819.3  1098.5   838.6  1106.1   857.8 1115.38   867.4  1118.6   963.8 1126.44
#Mann= 3 , 0 , 0
       0     .06       0   431.2    .045       0   446.2    .055       0
Bank Sta=431.2,446.2
XS Rating Curve= 0 ,0
Exp/Cntr=0.3,0.1

Type RM Length L Ch R = 1 ,6823.2  ,258.3,261.4,264.8
XS GIS Cut Line= 5
     1787556.746       284569.33     1787265.079       284569.33
      1787032.44      284586.691     1786834.523      284593.636
     1786633.134       284725.58
#Sta/Elev= 30
       0  1118.5   126.4 1090.61   136.1 1087.99     175 1074.78   184.7 1072.85
   204.2  1071.4   233.3 1066.74   262.5 1063.76   369.4 1060.06   388.9 1058.52
   422.6 1054.52   427.8 1054.29   437.6 1054.49   466.6 1055.44   515.2 1055.12
   600.4 1058.83     657 1059.72   685.3 1060.79   751.9 1064.91   761.5 1066.21
   771.1 1068.26   790.4 1073.85   819.3 1083.58   857.8 1099.71   867.4 1102.74
   877.1 1104.92   896.3 1108.29     906 1109.07   944.5 1109.64   963.8 1110.67
#Mann= 3 , 0 , 0
       0     .05       0   422.6    .045       0   437.6    .055       0
#XS Ineff= 2 , 0
                          469.02         1059.67
Permanent Ineff=
       F       F
Bank Sta=422.6,437.6
XS Rating Curve= 0 ,0
Exp/Cntr=0.3,0.1

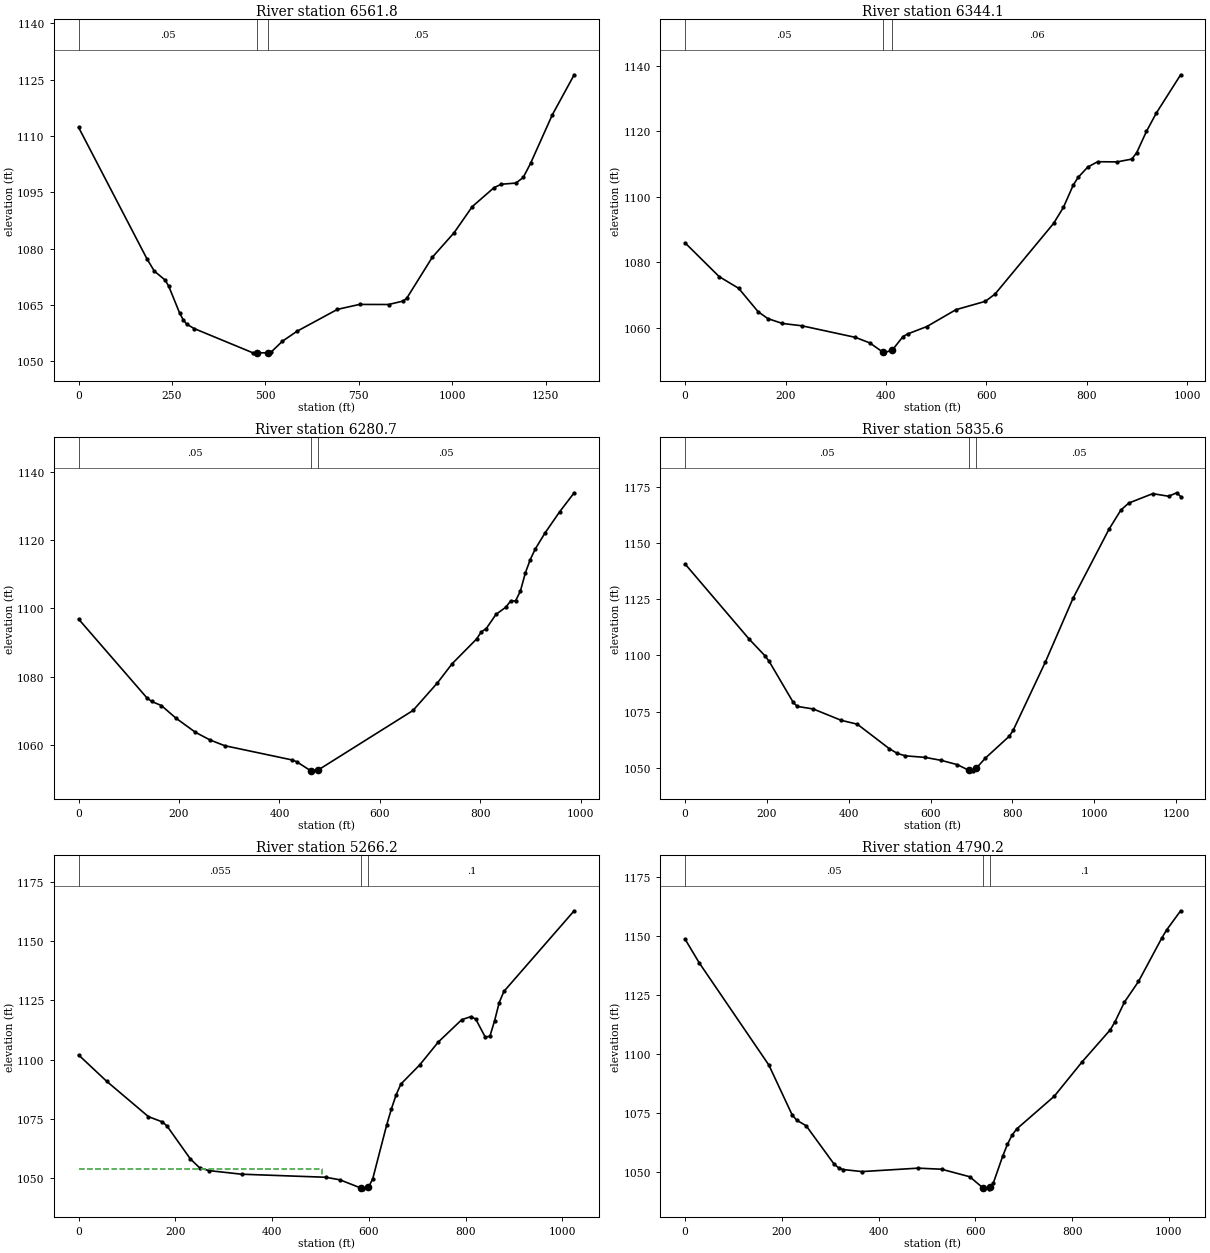
Type RM Length L Ch R = 1 ,6561.8  ,211,217.8,224.5
XS GIS Cut Line= 4
     1787562.068      284366.551     1787272.949      284353.532
      1786821.56      284318.809     1786246.908      284212.907
#Sta/Elev= 30
       0 1112.26   183.3 1077.23   202.6 1074.05   231.5 1071.66   241.2 1070.03
   270.1 1062.94   279.8 1061.11   289.4 1059.92   309.1 1058.77   466.6  1052.3
   476.4  1052.3   505.9 1052.31   515.8 1052.55   545.3 1055.37   584.7 1058.05
   692.9 1063.87   751.9 1065.18   829.8 1065.16   868.7 1066.08   878.5 1066.85
   946.6 1077.71  1005.1 1084.26  1053.8 1091.22  1112.2 1096.27  1131.7 1097.16
  1170.6 1097.47  1190.1 1098.96  1209.6 1102.68    1268 1115.63  1326.5 1126.28
#Mann= 3 , 0 , 0
       0     .05       0   476.4    .045       0   505.9     .05       0
Bank Sta=476.4,505.9
XS Rating Curve= 0 ,0
Exp/Cntr=0.3,0.1

Type RM Length L Ch R = 1 ,6344.1  ,63.4,63.4,63.4
XS GIS Cut Line= 4
     1787440.426      284282.872     1787120.982      284142.247
     1786989.037      284090.164     1786523.759      283918.289
#Sta/Elev= 30
       0 1085.93    67.9 1075.62   106.6 1072.06   145.4 1064.91   164.8  1062.8
   193.9 1061.31   232.7  1060.6   339.3 1057.06   367.9 1055.37   394.5 1052.48
   396.3 1052.34   412.9 1053.24   434.1 1057.33   443.6 1058.13   481.4 1060.37
   539.5 1065.53   597.9 1068.07   617.3  1070.3     734  1091.9   753.5  1096.8
   772.9 1103.54   782.6 1105.92   802.1 1109.11   821.6 1110.72   860.4 1110.67
   889.6 1111.52   899.4 1113.48   918.8 1119.99   938.3 1125.54   986.9 1137.28
#Mann= 3 , 0 , 0
       0     .05       0   394.5    .045       0   412.9     .06       0
Bank Sta=394.5,412.9
XS Rating Curve= 0 ,0
Exp/Cntr=0.3,0.1

Type RM Length L Ch R = 1 ,6280.7  ,440.7,445,449.5
XS GIS Cut Line= 4
     1787520.287      284246.414     1787200.843      284105.789
     1787068.898      284053.705     1786603.621       283881.83
#Sta/Elev= 30
       0 1096.84   135.7 1073.78   145.4 1072.68   164.8 1071.48   193.9 1067.77
   232.7 1063.62   261.8 1061.37   290.9  1059.7   424.7 1055.53   434.1 1055.01
   462.1 1052.35   462.5 1052.32   477.1 1052.57   665.9 1070.03   714.6 1078.13
   743.8 1083.74   792.4 1090.98   802.1 1093.11   811.8 1094.06   831.3 1098.25
   850.7 1100.32   860.4 1102.17   870.2 1102.18   879.9 1105.11   889.6 1110.36
   899.4  1114.3   909.1 1117.33   928.5 1122.04   957.7 1128.28   986.9 1133.91
#Mann= 3 , 0 , 0
       0     .05       0   462.1    .045       0   477.1     .05       0
Bank Sta=462.1,477.1
XS Rating Curve= 0 ,0
Exp/Cntr=0.3,0.1

Type RM Length L Ch R = 1 ,5835.6  ,557.4,569.5,581.4
XS GIS Cut Line= 3
     1787868.466       284018.54     1787281.797      283664.213
     1786837.834       283382.03
#Sta/Elev= 30
       0  1140.7   156.7 1107.24   195.8 1099.73   205.6 1097.32   264.4 1079.07
   274.2  1077.3   313.3 1076.15   381.8 1071.09     421 1069.38   499.3 1058.47
   518.9 1056.36   538.5  1055.3   587.5 1054.58   626.6 1053.26   665.8 1051.34
  693.24 1048.88   704.8 1048.61     712 1049.81   734.1 1054.28   792.5 1064.02
   802.3 1066.77   880.2 1096.85   948.4 1125.45  1036.1 1156.12  1065.3 1164.72
  1084.8 1167.85  1143.2 1172.02  1182.2 1170.86  1201.7 1172.41  1211.4 1170.74
#Mann= 3 , 0 , 0
       0     .05       0  693.24    .045       0     712     .05       0
Bank Sta=693.24,712
XS Rating Curve= 0 ,0
Exp/Cntr=0.3,0.1

Type RM Length L Ch R = 1 ,5266.2  ,476.6,475.9,475.2
XS GIS Cut Line= 4
     1787794.805      283730.701     1787631.886      283339.971
     1787517.708       283114.84     1787371.866      282798.408
#Sta/Elev= 30
       0 1101.92    57.7 1090.86   144.3 1075.88   173.2 1073.65   182.8  1071.9
   230.9 1058.04   250.2 1054.25   269.4  1053.1   336.7 1051.58   510.7 1050.29
   539.8 1049.22   584.1 1045.69   588.4  1045.4   599.1 1046.13   607.8 1049.58
   636.9 1072.53   646.6 1079.26   656.4 1085.18   666.1 1089.66   704.8 1097.69
   743.5 1107.42   791.9 1116.83   811.3 1118.16   820.9 1117.01   840.3 1109.51
     850 1109.81   859.7 1116.36   869.3 1124.08     879 1128.77  1024.2 1162.81
#Mann= 3 , 0 , 0
       0    .055       0   584.1    .045       0   599.1      .1       0
#XS Ineff= 2 , 0
           502.6 1053.59
Permanent Ineff=
       F       F
Bank Sta=584.1,599.1
XS Rating Curve= 0 ,0
Exp/Cntr=0.3,0.1

Type RM Length L Ch R = 1 ,4790.2  ,583.3,579.2,574.3
XS GIS Cut Line= 4
     1788255.927      283558.016     1788083.026      283171.599
     1787963.103      282949.474     1787809.182      282636.893
#Sta/Elev= 30
       0 1148.77    28.9 1138.81   173.2 1095.27   221.3  1074.1   230.9 1071.85
   250.2 1069.51   307.9 1053.24   317.5 1051.61   327.1  1050.9   365.6 1050.04
   481.6  1051.5   530.1 1051.04   588.4 1047.84   615.1 1043.19   627.2 1042.71
   630.1 1043.42   636.9 1045.08   656.4 1056.57   666.1 1061.58   675.8 1065.54
   685.4 1068.15   762.9 1082.03   820.9 1096.73     879 1110.33   888.7 1113.75
     908 1122.02   937.1  1130.8   985.5 1149.35   995.2 1152.69  1024.2 1160.84
#Mann= 3 , 0 , 0
       0     .05       0   615.1    .045       0   630.1      .1       0
Bank Sta=615.1,630.1
XS Rating Curve= 0 ,0
Exp/Cntr=0.3,0.1

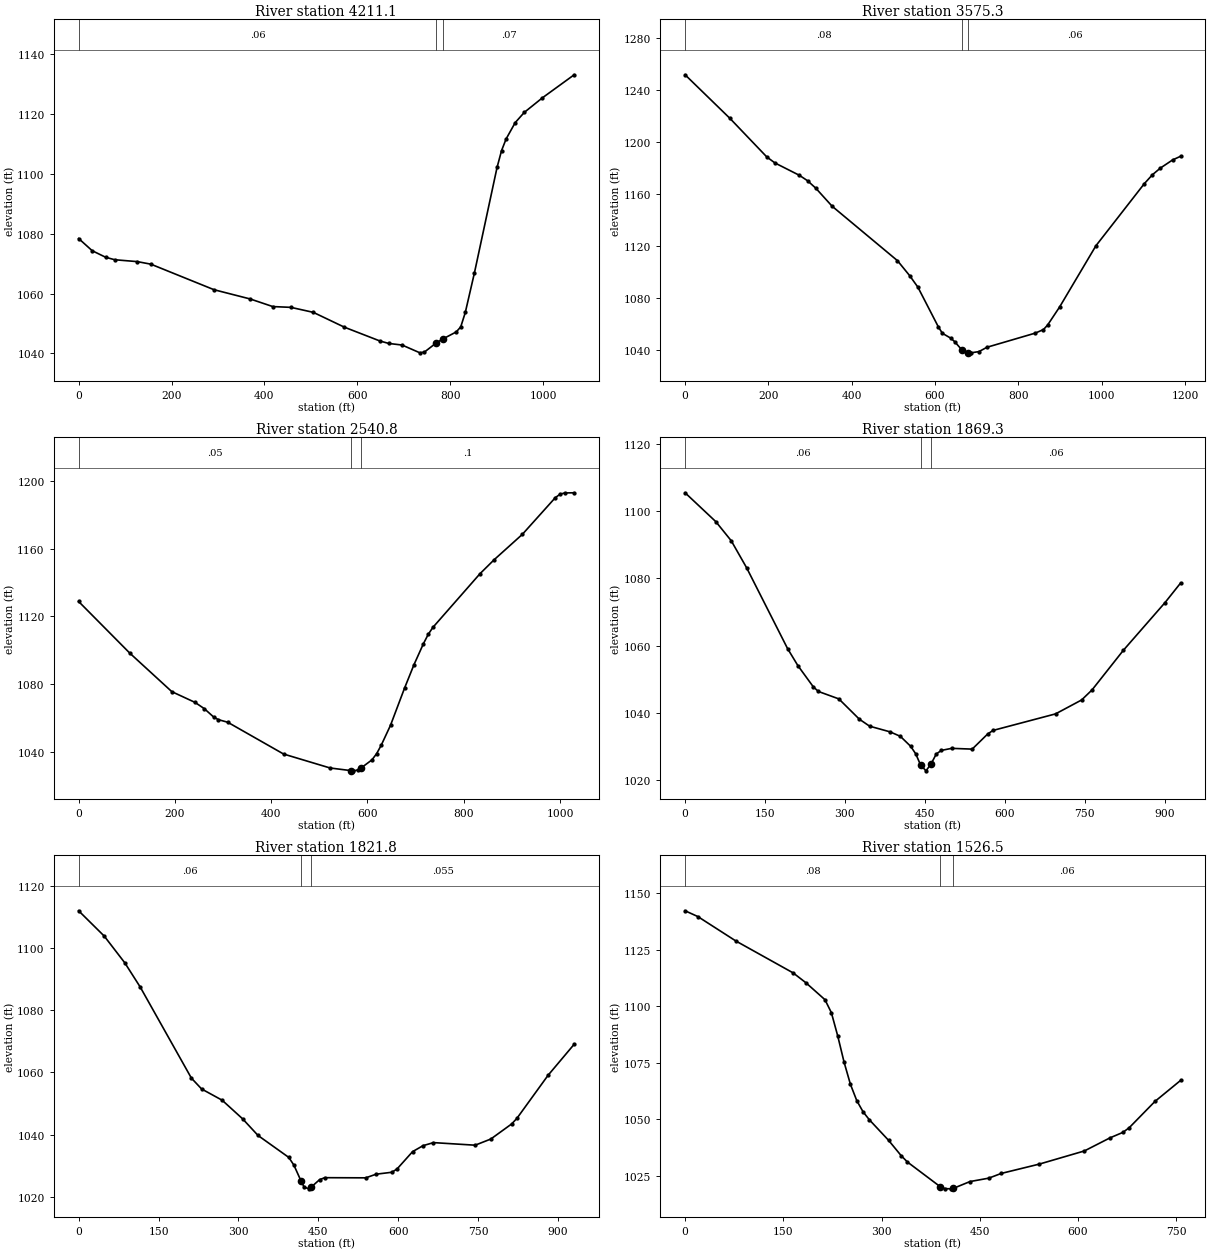
Type RM Length L Ch R = 1 ,4211.1  ,635.7,635.8,633.7
XS GIS Cut Line= 4
     1788873.785       283330.59     1788606.369      282924.731
     1788471.821      282727.248     1788250.467      282466.832
#Sta/Elev= 30
       0  1078.4    29.2 1074.32    58.3 1072.12    77.8  1071.3   126.4 1070.67
   155.5 1069.82   291.6 1061.27   369.4 1058.18     418 1055.64   456.9 1055.38
   505.2 1053.71   572.1 1048.75   648.5 1044.14   667.6 1043.31   696.3 1042.78
   734.8 1040.17   744.5 1040.44   770.4 1043.55   785.4 1044.92   812.9 1047.16
   822.6 1048.85   832.4 1053.66     852 1066.85   900.8 1102.18   910.5 1107.81
   920.3  1111.7   939.8 1117.14   959.4 1120.57   998.4 1125.44  1066.8 1133.15
#Mann= 3 , 0 , 0
       0     .06       0   770.4    .045       0   785.4     .07       0
Bank Sta=770.4,785.4
XS Rating Curve= 0 ,0
Exp/Cntr=0.3,0.1

Type RM Length L Ch R = 1 ,3575.3  ,1049.7,1034.4,1019.5
XS GIS Cut Line= 3
     1789444.736      282940.366     1789004.086      282440.172
     1788641.146      282063.663
#Sta/Elev= 30
       0 1251.92   107.8 1218.34   196.1 1188.75   215.7 1184.11   274.5 1174.59
   294.1 1170.41   313.7 1164.72   352.9 1150.85   509.8 1108.98   539.2 1097.41
   558.8 1088.62   607.8 1058.17   617.6 1053.13   637.2 1049.48     647 1046.76
   664.8 1040.21   679.8 1038.35     686  1038.1   705.4 1039.05   724.7 1042.39
   840.9 1053.29   860.3 1056.01     870 1059.36     899 1073.33   986.2 1120.43
  1102.4 1168.19  1121.8 1175.03  1141.1 1180.21  1170.2 1186.42  1189.6 1189.27
#Mann= 3 , 0 , 0
       0     .08       0   664.8    .045       0   679.8     .06       0
Bank Sta=664.8,679.8
XS Rating Curve= 0 ,0
Exp/Cntr=0.3,0.1

Type RM Length L Ch R = 1 ,2540.8  ,641.2,671.5,700.8
XS GIS Cut Line= 4
     1789727.897      281683.846     1789269.998      281605.721
     1789079.026      281577.509     1788707.932      281553.637
#Sta/Elev= 30
       0 1128.74   106.4 1098.23   193.6 1075.53   241.9 1069.18   261.3 1065.44
   280.6 1060.53   290.3 1059.01   309.7 1057.48   425.8 1038.71   522.4 1030.48
  566.29 1028.91   570.7  1028.8   580.3 1029.32   587.5 1030.65   609.3 1035.27
     619 1038.92   628.6 1043.92   647.9  1055.7   677.1 1077.66   696.7  1091.5
   716.3 1103.86   726.1 1109.28   735.8 1113.42   833.7 1145.12   863.1 1153.37
   921.8 1168.38   990.3 1190.04  1000.1 1192.06  1009.8  1192.8  1029.4  1192.9
#Mann= 3 , 0 , 0
       0     .05       0  566.29    .045       0   587.5      .1       0
Bank Sta=566.29,587.5
XS Rating Curve= 0 ,0
Exp/Cntr=0.3,0.1

Type RM Length L Ch R = 1 ,1869.3  ,47.5,47.6,47.5
XS GIS Cut Line= 4
     1789641.092      281512.405     1789563.184      281125.686
     1789544.954      280982.457     1789197.732      280801.901
#Sta/Elev= 30
       0 1105.49    57.7  1096.9    86.6 1091.22   115.5 1083.18   192.4 1059.13
   211.7 1054.08   240.5  1047.8   250.2 1046.39   288.6 1044.18   327.1 1038.14
   346.4 1036.06   384.9 1034.37   404.1 1033.04   423.4 1030.08     433 1027.82
     442 1024.53   452.2 1022.78   461.9 1024.89   471.5  1027.8   481.1 1028.86
   500.4 1029.47   538.9 1029.24   568.2 1033.77     578  1034.8   695.4 1039.72
   744.3 1043.86   763.9 1046.85   822.6 1058.62   900.9 1072.83   930.2 1078.66
#Mann= 3 , 0 , 0
       0     .06       0     442    .045       0   461.9     .06       0
Bank Sta=442,461.9
XS Rating Curve= 0 ,0
Exp/Cntr=0.3,0.1

Type RM Length L Ch R = 1 ,1821.8  ,328,295.3,261.4
XS GIS Cut Line= 4
     1789680.067      281468.915     1789602.159      281082.196
      1789583.93      280938.967     1789236.708      280758.412
#Sta/Elev= 30
       0 1111.98    48.1 1103.83    86.6 1095.25   115.5 1087.48   211.7 1058.14
   230.9 1054.65   269.4 1051.04   307.9 1045.04   336.8 1039.69   394.5 1032.64
   404.1 1030.15  417.71 1024.97   423.4 1023.06     433 1022.53   436.4 1023.07
   452.2 1025.47   461.9 1026.12   538.9 1026.07   558.4 1027.24   587.8 1027.86
   597.6  1028.9   626.9  1034.5   646.5 1036.42   666.1  1037.4   744.3 1036.57
   773.7 1038.55   812.8  1043.4   822.6 1045.18   881.3 1059.08   930.2 1069.04
#Mann= 3 , 0 , 0
       0     .06       0  417.71    .045       0   436.4    .055       0
Bank Sta=417.71,436.4
XS Rating Curve= 0 ,0
Exp/Cntr=0.3,0.1

Type RM Length L Ch R = 1 ,1526.5  ,223.6,180.2,133
XS GIS Cut Line= 4
     1789992.057      280815.573     1789672.613      280789.965
     1789491.189      280794.306     1789240.495      280748.689
#Sta/Elev= 30
       0 1142.17    19.4 1139.62    77.7 1128.78   165.1 1114.68   184.5 1110.34
   213.6 1102.84   223.4 1097.11   233.1 1086.81   242.8 1075.22   252.5 1065.42
   262.2 1058.19   271.9 1053.21   281.6 1049.67   310.8 1040.64     330 1033.86
   339.6 1031.04   389.6 1020.15   396.9 1019.28   406.4 1019.19   409.3 1019.36
   435.1 1022.41   463.7 1023.91   482.8    1026   541.2 1030.15   609.8 1035.95
     649 1041.75   668.6 1044.16   678.4 1046.26   717.6 1057.86   756.8 1067.16
#Mann= 3 , 0 , 0
       0     .08       0   389.6    .045       0   409.3     .06       0
Bank Sta=389.6,409.3
XS Rating Curve= 0 ,0
Exp/Cntr=0.3,0.1