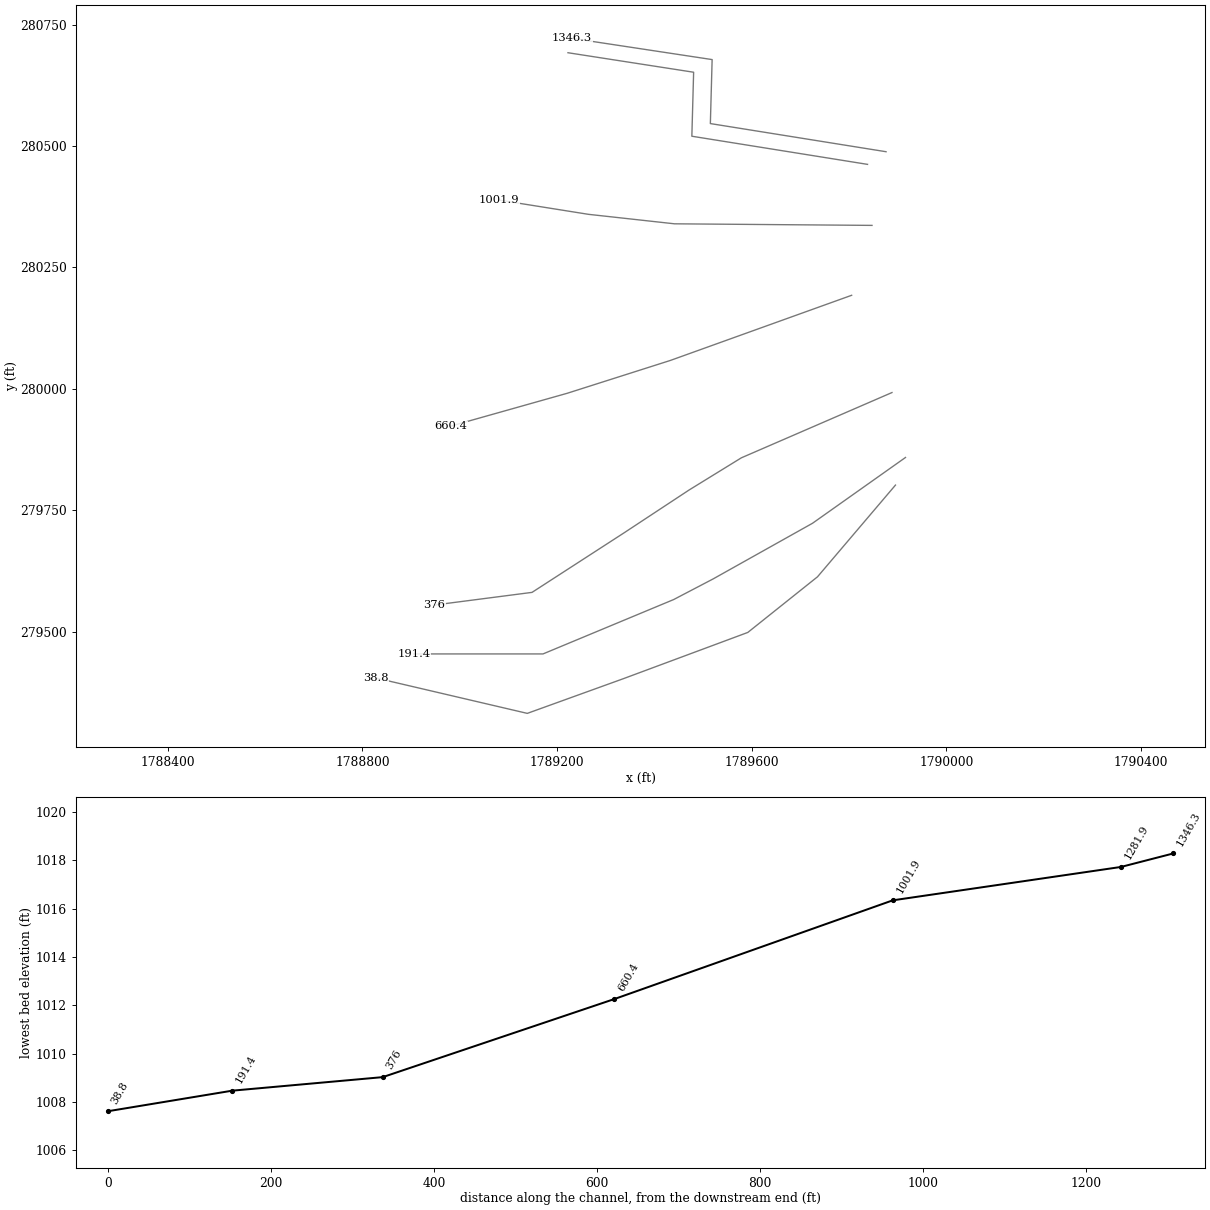
HEC-RAS study BerryRun.prj: BerryRun

--- BerryRun.g01 (geometry) --- (continued)

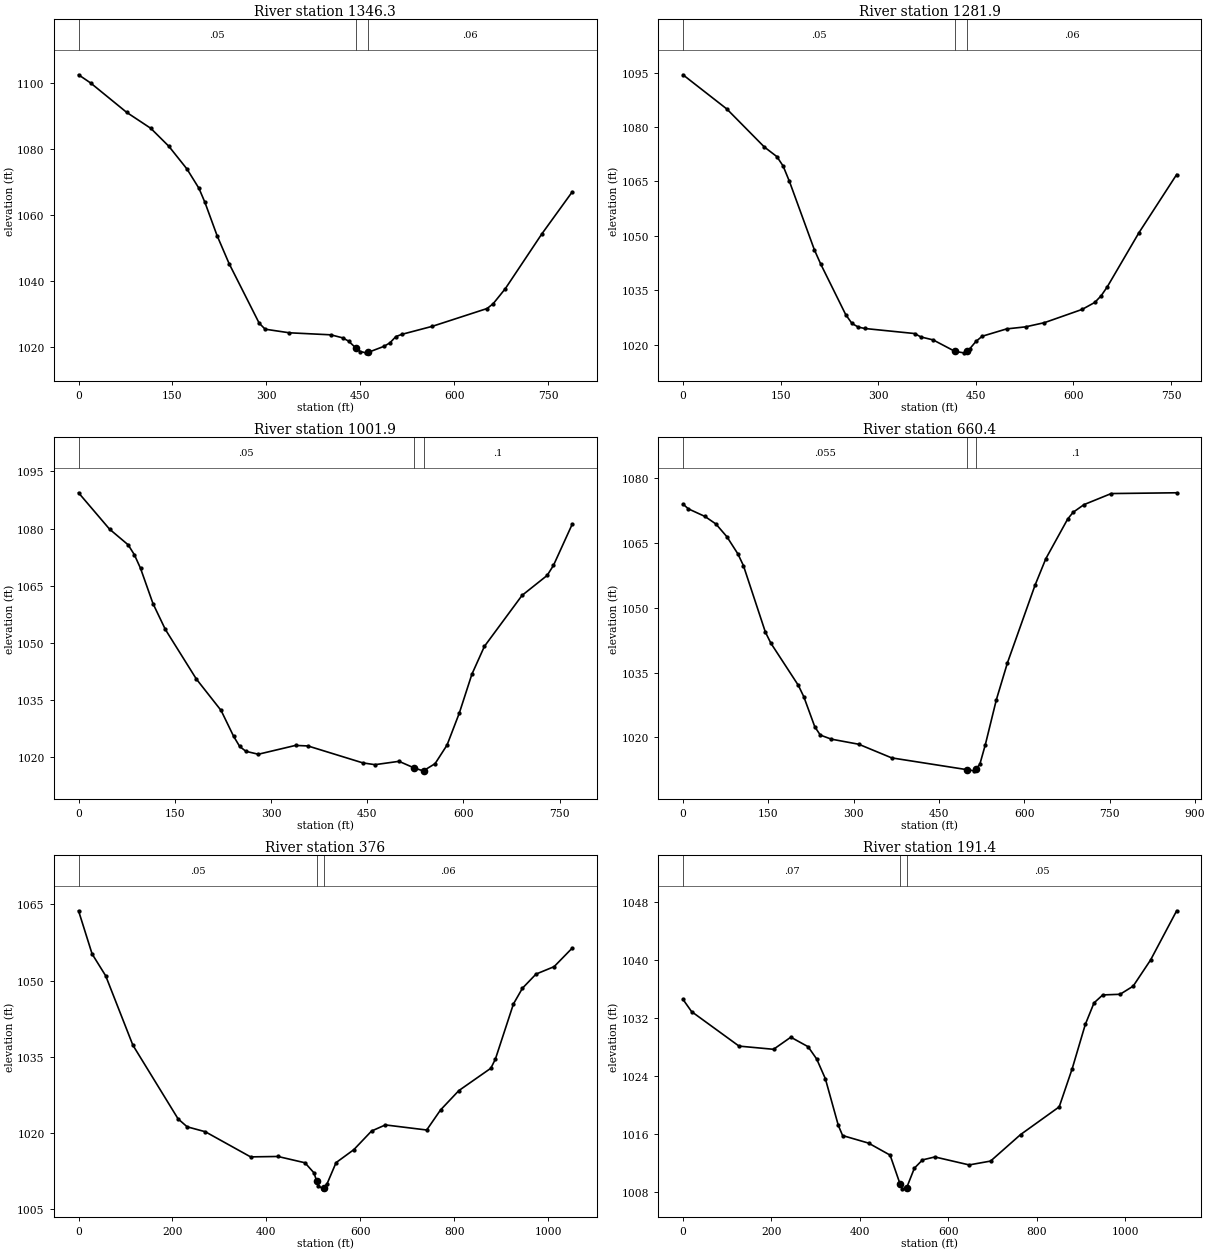
Type RM Length L Ch R = 1 ,1346.3  ,74.5,64.4,62.5
XS GIS Cut Line= 4
     1789875.955      280488.143     1789514.974      280546.085
      1789518.62      280677.856     1789230.599      280721.606
#Sta/Elev= 30
       0 1102.59    19.2 1100.12      77 1091.18   115.4 1086.36   144.3 1080.91
   173.2 1074.03   192.4 1068.16     202 1063.87   221.3 1053.85   240.5 1045.36
   288.6 1027.28   298.2 1025.45   336.7 1024.36   403.3 1023.74   422.1 1022.82
   431.5 1021.83     443 1019.77   450.3 1018.66   459.8 1018.28  463.03 1018.44
     488 1020.25   497.4 1021.29   507.1 1023.22   516.8  1023.9   565.4 1026.33
   652.8 1031.72   662.5 1033.18   681.9 1037.74   740.2 1054.33   788.8 1067.08
#Mann= 3 , 0 , 0
       0     .05       0     443    .045       0  463.03     .06       0
Bank Sta=443,463.03
XS Rating Curve= 0 ,0
Exp/Cntr=0.3,0.1

Type RM Length L Ch R = 1 ,1281.9  ,228.9,280,327.4
XS GIS Cut Line= 4
     1789837.934      280462.101     1789476.953      280520.044
     1789480.599      280651.814     1789222.439      280691.962
#Sta/Elev= 30
       0 1094.38    67.4 1084.95   125.1 1074.46   144.3 1071.82   153.9 1069.23
   163.6 1064.99     202  1046.1   211.7 1042.19   250.2 1028.22   259.8 1025.81
   269.4 1024.83     279 1024.44     356 1023.04   365.6  1022.1   384.4 1021.29
     418 1018.12   431.5 1017.72  436.33 1018.29   440.9 1018.87   450.3 1020.88
   459.8 1022.29   497.4 1024.32   526.4 1024.88   555.5 1026.04   613.5  1029.7
   632.9 1031.62   642.6 1033.44   652.2 1035.95   700.6  1050.8   758.7 1066.88
#Mann= 3 , 0 , 0
       0     .05       0     418    .045       0  436.33     .06       0
Bank Sta=418,436.33
XS Rating Curve= 0 ,0
Exp/Cntr=0.3,0.1

Type RM Length L Ch R = 1 ,1001.9  ,331.8,341.5,350.7
XS GIS Cut Line= 4
     1789847.135       280336.45     1789441.319      280339.705
     1789264.453      280359.236     1789081.076      280388.533
#Sta/Elev= 30
       0  1089.4    48.3 1079.85    77.3 1075.73      87 1073.13    96.6 1069.56
     116  1060.3   135.3 1053.49   183.6 1040.47   222.2  1032.2   241.6 1025.45
   251.2 1022.74   260.9 1021.47   280.2  1020.7   338.2 1023.02   357.5 1022.88
   443.3 1018.42     462 1017.96   499.5 1018.84     523 1017.11   536.9 1016.34
     538  1016.4   555.7 1018.22   574.4 1023.12   593.5 1031.52   613.1 1041.72
   632.6 1049.04   691.3 1062.44   730.4 1067.68   740.2  1070.3   769.5 1081.15
#Mann= 3 , 0 , 0
       0     .05       0     523    .045       0     538      .1       0
Bank Sta=523,538
XS Rating Curve= 0 ,0
Exp/Cntr=0.3,0.1

Type RM Length L Ch R = 1 ,660.4   ,277.8,284.4,291.7
XS GIS Cut Line= 4
     1789805.273      280192.519     1789432.878      280058.404
     1789220.638      279990.696     1788981.055      279922.988
#Sta/Elev= 30
       0 1074.04     9.6 1072.93    38.6 1071.18    57.9 1069.43    77.2 1066.48
    96.5 1062.51   106.2 1059.81   144.8  1044.4   154.5 1041.82   202.7 1032.07
   212.4 1029.41   231.7 1022.45   241.4 1020.54   260.7  1019.6   308.9 1018.42
   366.8 1015.26   499.6 1012.52     512 1012.26   514.6 1012.66   521.7 1013.77
   531.4 1018.34   550.8 1028.76   570.2 1037.27   618.6 1055.21   637.7  1061.4
     676 1070.56   685.6 1072.14   704.8 1073.92   752.6 1076.48   867.6 1076.66
#Mann= 3 , 0 , 0
       0    .055       0   499.6    .045       0   514.6      .1       0
Bank Sta=499.6,514.6
XS Rating Curve= 0 ,0
Exp/Cntr=0.3,0.1

Type RM Length L Ch R = 1 ,376     ,187.3,184.6,181.3
XS GIS Cut Line= 6
     1789888.151      279992.266     1789578.711      279857.884
     1789471.484      279791.745      1789337.37      279703.203
     1789148.568      279580.807     1788948.047      279554.766
#Sta/Elev= 30
       0 1063.76    28.9 1055.26    57.8 1050.96   115.7 1037.31     212  1022.8
   231.3 1021.24   269.9 1020.27   366.4 1015.32   424.6  1015.4   482.2 1014.16
   501.2 1012.19   507.1 1010.59   510.6 1009.64   520.1 1009.03   522.1 1009.25
   529.5 1010.08   548.4 1014.19   586.2 1016.74     624 1020.41   653.4 1021.61
   741.4 1020.61   770.8 1024.55   809.9 1028.37   877.9 1032.76   887.6 1034.55
   926.1 1045.42   945.3 1048.52   974.2  1051.3  1012.7 1052.76  1051.3 1056.42
#Mann= 3 , 0 , 0
       0     .05       0   507.1    .045       0   522.1     .06       0
Bank Sta=507.1,522.1
XS Rating Curve= 0 ,0
Exp/Cntr=0.3,0.1

Type RM Length L Ch R = 1 ,191.4   ,150.5,152.6,150.5
XS GIS Cut Line= 6
     1789915.929      279858.585     1789724.957      279723.169
     1789520.638      279608.491     1789439.605      279566.043
     1789171.137      279454.071     1788905.512      279454.071
#Sta/Elev= 30
       0 1034.61    19.5 1032.92   126.8 1028.16   204.8 1027.72   243.9 1029.39
   282.9 1028.08   302.4 1026.38     322 1023.66   351.3 1017.22     361 1015.82
   419.6 1014.78   468.4 1013.12   490.7 1009.18   495.9 1008.47   505.7  1008.6
   523.3 1011.32   541.6 1012.46   569.6 1012.87   647.2 1011.77   695.6  1012.3
   763.5 1015.96   850.8 1019.78   880.3 1025.07   909.8 1031.15   929.5 1034.12
   949.2 1035.22   988.5 1035.31    1018 1036.43  1057.4 1040.04  1116.4 1046.83
#Mann= 3 , 0 , 0
       0     .07       0   490.7    .045       0   505.7     .05       0
Bank Sta=490.7,505.7
XS Rating Curve= 0 ,0
Exp/Cntr=0.3,0.1

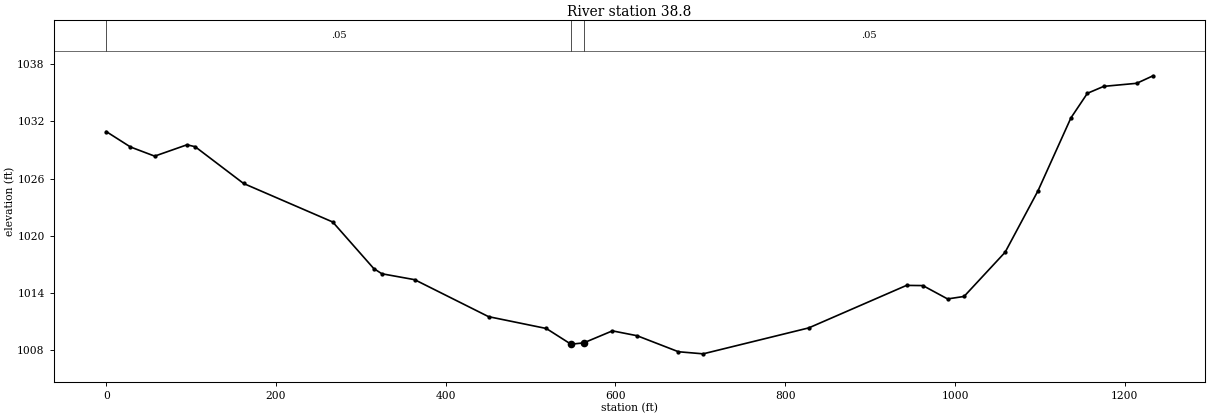
Type RM Length L Ch R = 1 ,38.8    ,37.3,38.8,44.5
XS GIS Cut Line= 6
     1789895.334       279801.72     1789735.178      279612.918
     1789591.949      279498.335      1789336.74      279403.283
     1789138.824      279331.668     1788827.626      279404.585
#Sta/Elev= 30
       0 1030.94    28.6 1029.32    57.1 1028.36    95.2 1029.55   104.8 1029.35
   161.9 1025.49   266.9 1021.45   315.2 1016.57   324.8 1016.02   363.4  1015.4
   450.5 1011.52   518.5 1010.28   547.6 1008.63   562.6 1008.77   596.4 1010.03
   625.5 1009.52   674.2 1007.84   703.3 1007.62   827.7 1010.34   942.9  1014.8
   962.2 1014.78   991.3 1013.38  1010.7 1013.64  1059.1 1018.28  1097.8 1024.72
  1136.6 1032.37    1156 1034.95  1175.3 1035.68  1214.1    1036  1233.4 1036.79
#Mann= 3 , 0 , 0
       0     .05       0   547.6    .045       0   562.6     .05       0
Bank Sta=547.6,562.6
XS Rating Curve= 0 ,0
Exp/Cntr=0.3,0.1

Chan Stop Cuts=-1
Use User Specified Reach Order=0
Composite Channel Slope=5